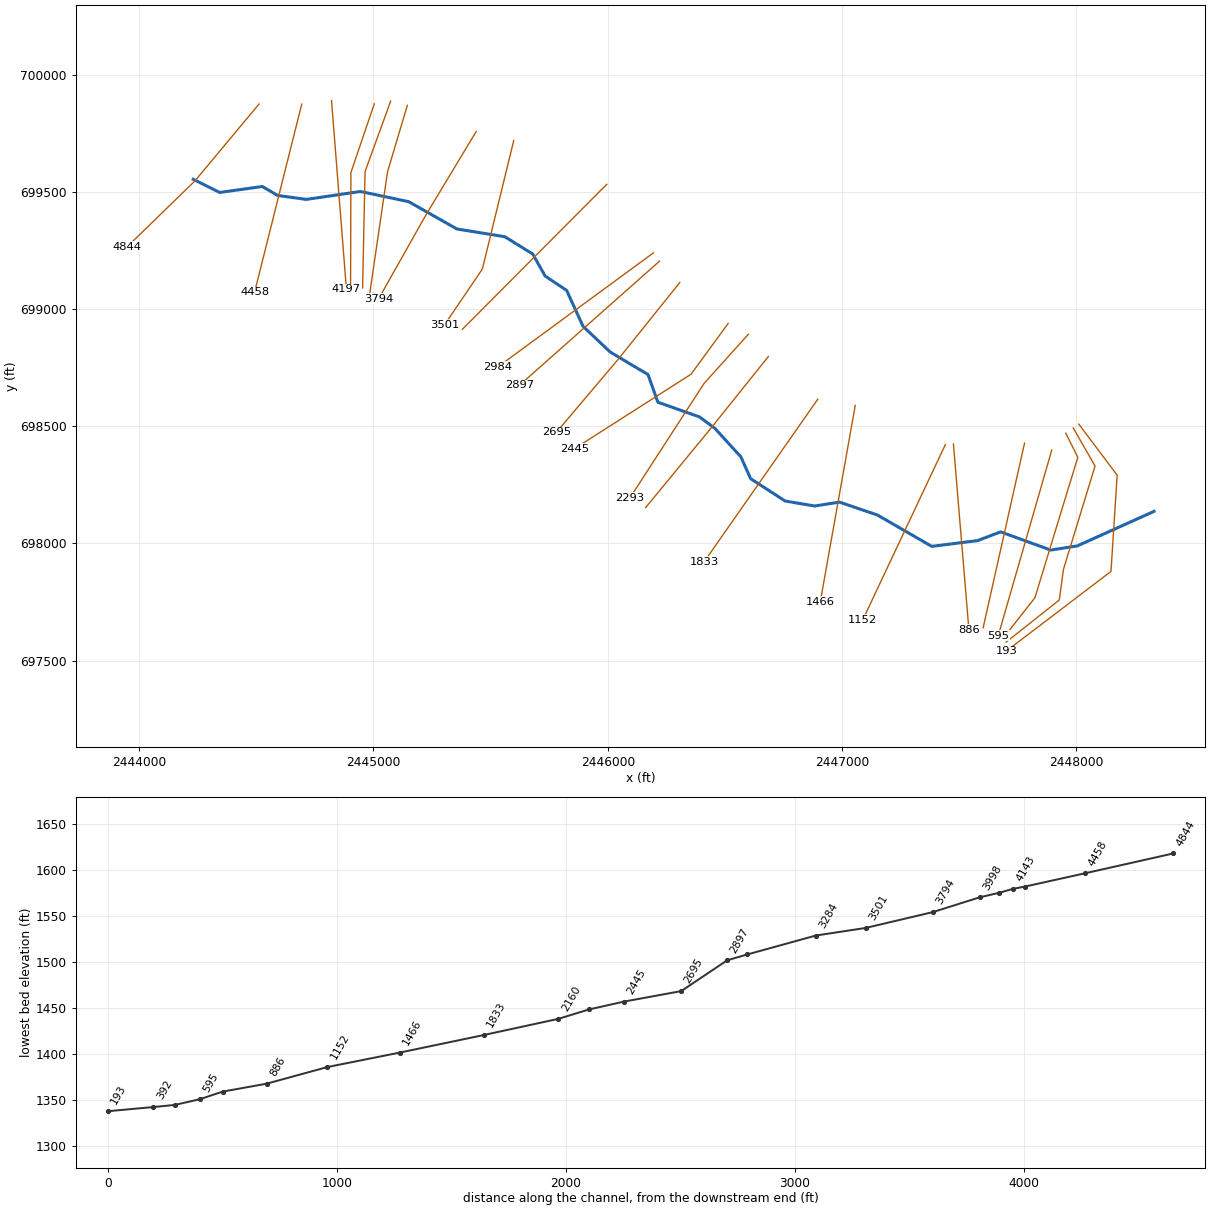
--- ZEKERN.prj (project) ---

Proj Title=ZEKERN
Current Plan=p01
Default Exp/Contr=0,0
English Units
Geom File=g01
Flow File=f01
Plan File=p01
BEGIN DESCRIPTION:
Stream Name: Zeke Run
Flood Zone: Approximate
Pendleton County, West Virginia
HEC-RAS Version: 5.0.7
Hydrology Method:
Regression equation
END DESCRIPTION:
DSS Export Rating Curves= 0
DSS Export Rating Curve Sorted= 0
DSS Export Volume Flow Curves= 0
DXF OffsetX= 0
DXF OffsetY= 0
DXF ScaleX= 0
DXF ScaleY= 0

--- ZEKERN.p01 (plan) ---

Plan Title=Floodplain
Program Version=5.07
Short Identifier=Floodplain
Geom File=g01
Flow File=f01
Subcritical Flow
K Sum by GR= 0
Std Step Tol= 0.01
Critical Tol= 0.01
Num of Std Step Trials= 20
Max Error Tol= 0.3
Flow Tol Ratio= 0.001
Split Flow NTrial= 30
Split Flow Tol= 0.02
Split Flow Ratio= 0.02
Log Output Level= 0
Friction Slope Method= 1
Unsteady Friction Slope Method= 2
Unsteady Bridges Friction Slope Method= 1
Parabolic Critical Depth
Global Vel Dist= 0 , 0 , 0
Global Log Level= 0
CheckData=True
Encroach Param=-1 ,0,0, 0
Mapping Interval=1HOUR
Computation Time Step Use Courant=        0
Computation Time Step Use Time Series=    0
Computation Time Step Count To Double=0
Computation Time Step Max Doubling=0
Computation Time Step Max Halving=0
Computation Time Step Residence Courant=0
Run HTab= 0
Run UNet= 0
Run Sediment= 0
Run PostProcess= 0
Run WQNet= 0
Run RASMapper= 0
UNET Theta= 0
UNET Theta Warmup= 0
UNET ZTol= 0
UNET ZSATol= 0
UNET MxIter= 0
UNET Max Iter WO Improvement= 0
UNET MaxInSteps= 0
UNET DtIC= 0
UNET DtMin= 0
UNET MaxCRTS= 0
UNET WFStab= 0
UNET SFStab= 0
UNET WFX= 1
UNET SFX= 1
UNET 1D Methodology=Finite Difference
UNET DSS MLevel= 1
UNET Pardiso=0
UNET DZMax Abort= 0
UNET Use Existing IB Tables= 0
UNET Froude Reduction=False
UNET Froude Limit= 0
UNET Froude Power= 0
UNET D1 Cores= 0
UNET D2 Coriolis=0
UNET D2 Cores= 0
UNET D2 Theta= 1
UNET D2 Theta Warmup= 1
UNET D2 Z Tol= 0.01
UNET D2 Volume Tol= 0.01
UNET D2 Max Iterations= 20
UNET D2 Equation= 0
UNET D2 RampUpFraction=0.1
UNET D2 TimeSlices= 1
UNET D2 BCVolumeCheck=0
UNET D1D2 MaxIter= 0
UNET D1D2 ZTol=0.01
UNET D1D2 QTol=0.1
UNET D1D2 MinQTol=1
Write IC File= 0
Write IC File at Fixed DateTime=0
Write IC File at Sim End=0
Echo Input=False
Echo Parameters=False
Echo Output=False
Write Detailed= 0
HDF Write Warmup=0
HDF Write Time Slices=0
HDF Flush=0
HDF Face Node Velocities=0
HDF Compression= 1
HDF Chunk Size= 1
HDF Spatial Parts= 1
HDF Use Max Rows=0
HDF Fixed Rows= 1
Calibration Method= 0
Calibration Iterations= 20
Calibration Max Change=0.05
Calibration Tolerance=0.2
Calibration Maximum=1.5
Calibration Minimum=0.5
Calibration Optimization Method= 1
WQ AD Non Conservative
WQ ULTIMATE=-1
WQ Max Comp Step=1HOUR
WQ Output Interval=15MIN
WQ Output Selected Increments= 0
WQ Output face flow=0
WQ Output face velocity=0
WQ Output face area=0
WQ Output face dispersion=0
WQ Output cell volume=0
WQ Output cell surface area=0
WQ Output cell continuity=0
WQ Output cumulative cell continuity=0
WQ Output face conc=0
WQ Output face dconc_dx=0
WQ Output face courant=0
WQ Output face peclet=0
WQ Output face adv mass=0
WQ Output face disp mass=0
WQ Output cell mass=0
WQ Output cell source sink temp=0
WQ Output nsm pathways=0
WQ Output nsm derived pathways=0
WQ Output MaxMinRange=-1
WQ Daily Max Min Mean=-1
WQ Daily Range=0
WQ Daily Time=0
WQ Create Restart=0
WQ Fixed Restart=0
WQ System Summary=0
WQ Write To DSS=0
WQ Use Fixed Temperature=0
Sorting and Armoring Iterations= 10
XS Update Threshold= 0.02
Bed Roughness Predictor= 0
Hydraulics Update Threshold= 0.02
Energy Slope Method= 1
Volume Change Method= 1
Sediment Retention Method= 0
XS Weighting Method= 0
Number of US Weighted Cross Sections= 1
Number of DS Weighted Cross Sections= 1
Upstream XS Weight=0
Main XS Weight=1
Downstream XS Weight=0
Number of DS XS's Weighted with US Boundary= 1
Upstream Boundary Weight= 1
Weight of XSs Associated with US Boundary= 0
Number of US XS's Weighted with DS Boundary= 1
Downstream Boundary Weight= 0.5
Weight of XSs Associated with DS Boundary= 0.5
Percentile Method= 0
Sediment Output Level= 3
Mass or Volume Output= 0
Output Increment Type= 1
Profile and TS Output Increment= 1
XS Output Flag= 0
XS Output Increment= 10
Write Gradation File= 0
Read Gradation Hotstart= 0
Write HDF5 File= 1
Write Binary Output= 1
Write DSS Sediment File= 0
SV Curve= 0
Specific Gage Flag= 0

--- ZEKERN.f01 (steady flow) ---

Flow Title=Flows
Program Version=5.07
Number of Profiles= 6
Profile Names=P100yr,P10yr,P25yr,P50yr,P500yr,P101yr
River Rch & RM=ZEKERN,Main            ,4844
     551     258     365     455     808     671
River Rch & RM=ZEKERN,Main            ,3284
     616     288     407     508     903     750
Boundary for River Rch & Prof#=ZEKERN,Main            , 1
Up Type= 0
Dn Type= 3
Dn Slope=0.02238
Boundary for River Rch & Prof#=ZEKERN,Main            , 2
Up Type= 0
Dn Type= 3
Dn Slope=0.02238
Boundary for River Rch & Prof#=ZEKERN,Main            , 3
Up Type= 0
Dn Type= 3
Dn Slope=0.02238
Boundary for River Rch & Prof#=ZEKERN,Main            , 4
Up Type= 0
Dn Type= 3
Dn Slope=0.02238
Boundary for River Rch & Prof#=ZEKERN,Main            , 5
Up Type= 0
Dn Type= 3
Dn Slope=0.02238
Boundary for River Rch & Prof#=ZEKERN,Main            , 6
Up Type= 0
Dn Type= 3
Dn Slope=0.02238
DSS Import GetInterval= 0
DSS Import GetPeak= 0
DSS Import FillOption= 0

--- ZEKERN.g01 (geometry) ---

Geom Title=Geometry
Program Version=5.07

River Reach=ZEKERN          ,Main
Reach XY= 30
2444230.83500001699554.4160000092444343.75700003699498.109999999
2444525.54600003699523.6239999982444591.34200004      699485.287
2444713.96000001699468.5779999942444944.21300003699502.357999995
2445150.26800001699458.8599999992445356.18300003699342.340000004
2445560.55900002699309.2880000172445679.52599999699235.611000001
2445732.81299999699141.2820000052445824.55599999699080.121000007
2445894.23900002698927.1089999972446009.88500002698817.497999996
     2446171.734698720.939999998     2446213.831698602.878000021
2446391.08300003698540.3639999932446457.49900001698491.084000021
2446567.98000002698369.7570000142446609.71200004698276.638999999
2446757.06800002698181.1589999942446882.69600004698159.988000005
2446988.66400003 698176.571000012447150.81099999698121.498000011
2447382.73100001697987.7020000222447578.73400003698012.417999998
2447676.56999999698049.4920000142447890.31799999697971.914000005
     2448003.708697989.5869999982448331.58497962698137.235289544

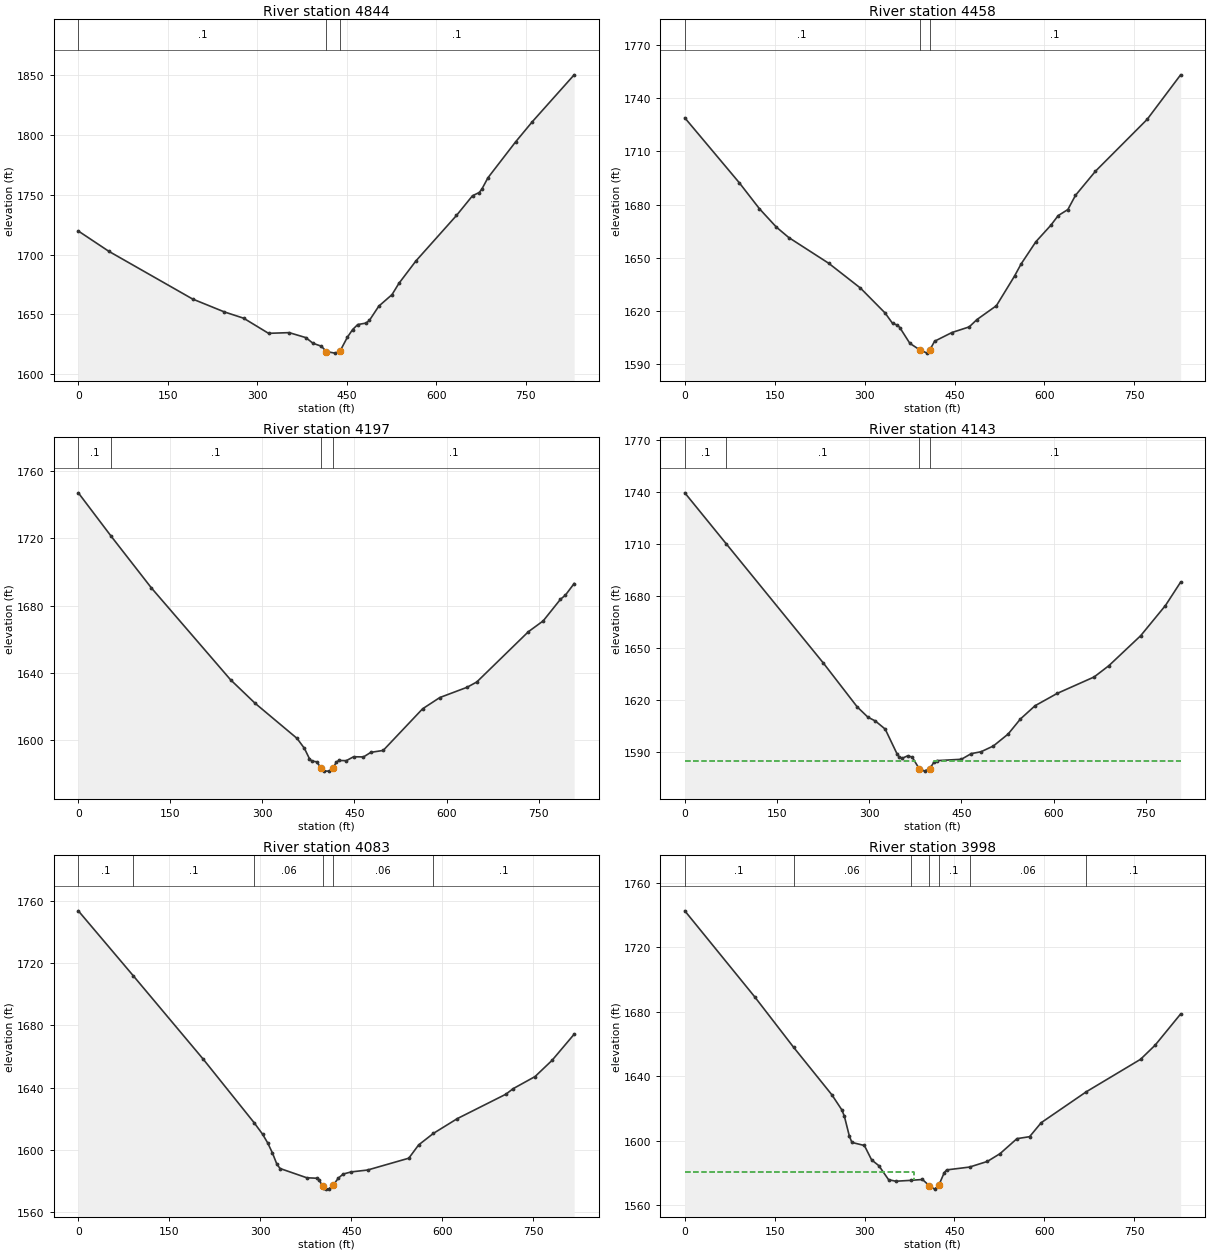
Type RM Length L Ch R = 1 ,4844    ,386.4,386.4,386.4
XS GIS Cut Line= 3
2444511.51678112699875.693045907     2444237.578      699547.033
     2443948.624      699266.186
#Sta/Elev= 30
       0 1719.77    51.2 1702.78   191.4 1662.94   244.9  1652.1     277 1646.88
   318.7 1634.24   353.3 1634.82   381.2 1630.66     393 1625.99   407.2 1623.45
   415.8 1618.97     430 1617.69   438.4 1619.27     451 1631.15   459.7 1637.44
   468.2 1641.58     482 1642.79   487.6 1644.98   503.5 1656.99   525.6 1666.59
   537.1 1675.97   565.7 1694.78   633.6 1732.76   660.5 1749.27   671.7 1751.95
   676.1 1754.76   686.3 1764.26   732.6 1794.23   760.9 1811.26   830.8 1850.34
#Mann= 3 ,-1 , 0
       0      .1       0   415.8    .045       0   438.4      .1       0
Bank Sta=415.8,438.4
XS Rating Curve= 0 ,0
Exp/Cntr=0.3,0.1

Type RM Length L Ch R = 1 ,4458    ,260.8,260.8,260.8
XS GIS Cut Line= 2
2444693.72934243699875.054243046 2444492.6745591 699072.80875847
#Sta/Elev= 30
       0 1728.99    90.9 1692.32   124.6  1677.6   152.7 1667.28   173.4 1661.38
     240 1646.85     293 1632.83   334.2 1618.72   346.6 1612.87   354.8 1611.89
   358.7  1610.5   375.4 1601.62   391.7 1597.98   404.3 1596.08   408.4 1597.69
   416.7  1602.8   445.5  1607.7   474.4  1610.9   487.3 1615.03   519.8 1622.87
     550 1639.58     561 1646.45   585.7 1659.03   610.5 1668.27   622.8 1673.74
     639 1677.18   651.7  1685.2   685.1 1698.85   771.3 1728.13   827.1 1753.28
#Mann= 3 ,-1 , 0
       0      .1       0   391.7    .045       0   408.4      .1       0
Bank Sta=391.7,408.4
XS Rating Curve= 0 ,0
Exp/Cntr=0.3,0.1

Type RM Length L Ch R = 1 ,4197    ,53.8,53.8,53.8
XS GIS Cut Line= 2
2444820.98653034      699890.1442444884.52756904699084.666019877
#Sta/Elev= 30
       0 1747.08   53.811721.139   119.2 1690.53     248 1636.05   288.1 1622.05
   356.4  1601.2   368.4 1595.29   376.6 1589.16   380.4 1587.73   388.5 1587.28
   395.2 1583.76   400.5 1581.79   408.5 1581.75   415.11583.754   420.6 1587.16
   424.6 1588.09   436.6 1587.96   448.6 1590.29   464.7 1590.18   476.7 1592.91
   496.8 1594.04     561 1618.77   589.1 1625.47   633.3 1631.53   649.3  1634.7
   733.4 1664.57   757.6 1671.02   785.7 1683.84   793.7 1686.28     808 1693.21
#Mann= 4 ,-1 , 0
       0      .1       0   53.81      .1       0   395.2    .045       0
   415.1      .1       0
Bank Sta=395.2,415.1
XS Rating Curve= 0 ,0
Exp/Cntr=0.5,0.3

Type RM Length L Ch R = 1 ,4143    ,59.7,59.7,59.7
XS GIS Cut Line= 3
2445003.44890378699876.4363989632444903.58658043699582.912081004
2444902.27354916699086.144462351
#Sta/Elev= 30
       0 1739.79   67.851710.196   225.5 1641.54   280.5 1616.27   298.1 1610.27
     310 1608.14   326.1 1603.43   345.3 1589.18   349.3  1587.2   354.1 1586.68
   362.8 1588.04   370.1 1587.23   381.4 1580.58   390.1 1579.18   398.7 1580.67
   406.1 1584.72   410.1 1585.23   450.1 1586.02   466.1 1589.28   482.1 1590.37
   502.1 1593.69   526.1 1600.57   546.1 1609.26   569.9 1616.91     606 1624.04
   666.1 1633.53   690.1 1640.05   741.8 1657.34   782.1 1674.76   806.8 1688.26
#Mann= 4 ,-1 , 0
       0      .1       0   67.85      .1       0   381.4    .045       0
   398.7      .1       0
#XS Ineff= 2 , 0
          374.97 1585.16  406.14         1584.83
Permanent Ineff=
       F       F
Bank Sta=381.4,398.7
XS Rating Curve= 0 ,0
Exp/Cntr(USF)=0,0
Exp/Cntr=0.5,0.3

Type RM Length L Ch R = 1 ,4083    ,85.7,85.7,85.7
XS GIS Cut Line= 3
     2445073.469      699888.1382444964.10293254699587.524553004
2444953.57748884699090.419326882
#Sta/Elev= 30
       0 1753.53   90.861711.714     206 1658.26   289.7 1617.57   303.5 1610.27
   312.1 1604.58   319.9 1598.13   327.3 1590.85   332.5 1588.18   376.5 1582.24
   392.5 1581.95   396.5 1580.96   402.51577.005   404.5 1575.73   408.5 1574.95
   412.5 1575.03   419.8 1577.37   428.5 1582.03   436.5 1584.63   449.9 1586.01
   476.6  1587.2   544.6  1594.8   560.8 1603.32  585.241610.744   624.6 1620.21
   704.6 1635.86   716.6 1639.42   752.6 1647.17   780.6 1657.55   817.1 1674.36
#Mann= 6 ,-1 , 0
       0      .1       0   90.86      .1       0   289.7     .06       0
   402.5    .045       0   419.8     .06       0  585.24      .1       0
Bank Sta=402.5,419.8
XS Rating Curve= 0 ,0
Exp/Cntr=0.5,0.3

Type RM Length L Ch R = 1 ,3998    ,203.5,203.5,203.5
XS GIS Cut Line= 3
     2445144.555      699870.0862445060.01729362699586.314570708
     2444983.119      699060.734
#Sta/Elev= 30
       0 1742.68   116.6 1689.33  181.421658.055   245.4  1628.5   262.1 1619.12
   266.3 1615.14   274.6 1602.84   278.8 1598.96   299.6 1597.05   311.7 1588.13
   323.8 1584.51     340 1575.84   352.1 1574.87  377.551575.427   396.6 1575.95
   407.6 1572.19   416.8 1569.97   423.7 1572.28     433 1580.28     437  1581.9
   475.11583.662   504.8 1587.15   525.9 1591.96   554.2 1601.29   575.3 1602.52
   594.7 1611.21  670.191630.453   760.4 1650.53   784.7 1659.28   827.3 1678.66
#Mann= 7 ,-1 , 0
       0      .1       0  181.42     .06       0  377.55      .1       0
   407.6    .045       0   423.7      .1       0   475.1     .06       0
  670.19      .1       0
#XS Ineff= 2 , 0
          383.22 1580.29
Permanent Ineff=
       F       F
Bank Sta=407.6,423.7
XS Rating Curve= 0 ,0
Exp/Cntr=0.3,0.1

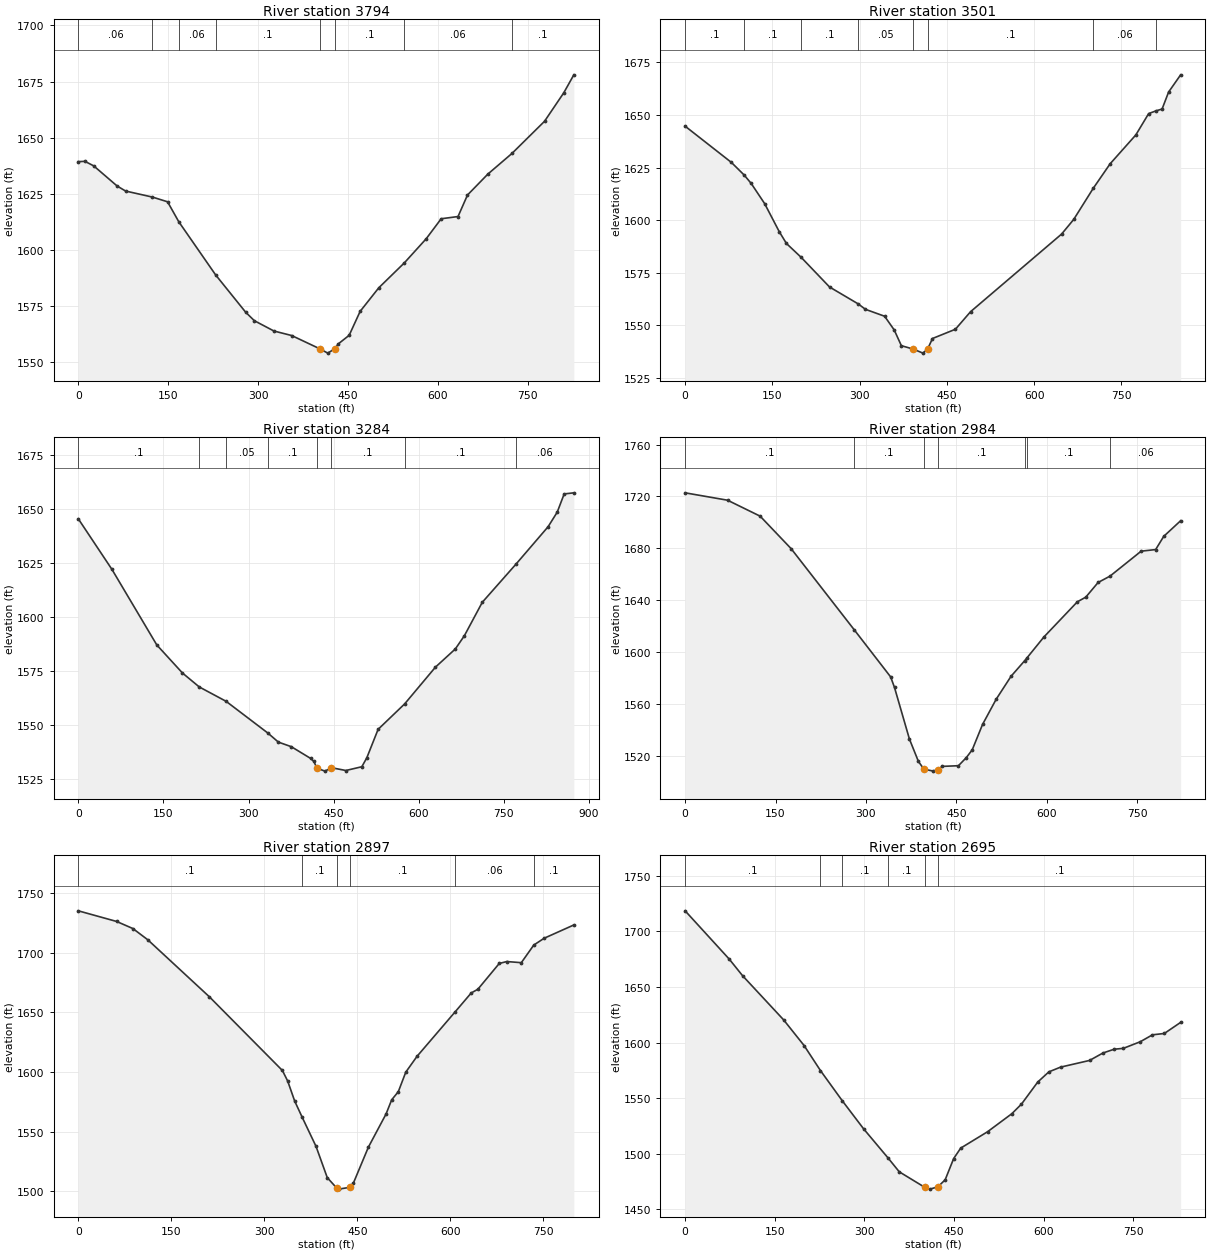
Type RM Length L Ch R = 1 ,3794    ,293.6,293.6,293.6
XS GIS Cut Line= 3
     2445438.461      699758.436     2445222.517      699400.012
     2445022.153      699044.305
#Sta/Elev= 30
       0 1639.33    11.1 1639.46    25.7 1637.44    64.8 1628.46    78.9 1626.23
  123.751623.532   148.9 1621.44  167.621612.542  229.131588.853   279.2 1572.24
   293.7 1568.46   326.4 1563.86     356 1561.85   402.5 1555.99   416.2 1554.01
   427.9 1555.95   433.8 1558.14   451.9 1561.96   470.2 1572.62   501.3 1583.12
  543.821594.189   580.4 1604.97   605.4 1613.88   633.5 1614.87   649.3 1624.46
   683.4 1633.81  723.471642.977   777.8  1657.3     810 1670.03   826.7 1678.01
#Mann= 8 ,-1 , 0
       0     .06       0  123.75     .05       0  167.62     .06       0
  229.13      .1       0   402.5    .045       0   427.9      .1       0
  543.82     .06       0  723.47      .1       0
Bank Sta=402.5,427.9
XS Rating Curve= 0 ,0
Exp/Cntr=0.3,0.1

Type RM Length L Ch R = 1 ,3501    ,216.7,216.7,216.7
XS GIS Cut Line= 3
     2445598.706      699720.1152445464.86725418 699171.61842885
2445303.49678347698933.789549164
#Sta/Elev= 30
       0 1644.68    79.5 1627.46  101.651621.408   113.5 1617.49   136.7 1607.87
   161.8 1594.54   174.2 1588.91  199.551582.306   248.3 1568.22  297.441560.201
   310.1 1557.59     343 1554.31   359.5 1547.79   371.8 1540.31   392.4 1538.68
   408.9 1536.77   417.1  1538.8   425.3 1543.72   464.7 1548.12   490.8 1556.47
   647.3 1593.38   668.1 1600.32  701.771615.164   730.8 1626.81     775 1640.54
     797 1650.67  809.681651.971   820.1 1652.84   831.3 1660.91     852  1669.1
#Mann= 8 ,-1 , 0
       0      .1       0  101.65      .1       0  199.55      .1       0
  297.44     .05       0   392.4    .045       0   417.1      .1       0
  701.77     .06       0  809.68      .1       0
Bank Sta=392.4,417.1
XS Rating Curve= 0 ,0
Exp/Cntr=0.3,0.1

Type RM Length L Ch R = 1 ,3284    ,300,300,300
XS GIS Cut Line= 2
2445995.56851257699532.8805868082445379.41413703698914.214549164
#Sta/Elev= 30
       0 1645.25    59.3 1621.85   138.3 1586.93   183.5 1573.96  213.081567.519
   260.4 1560.87  333.731546.247   352.6 1541.99   375.3 1539.89   409.3 1534.47
   414.9 1533.12   420.6 1529.95   420.6 1529.93   420.6 1529.92   434.7 1528.58
   446.1 1530.16   471.5 1528.87   499.6 1530.61   508.3 1534.68   528.3  1547.9
  575.031559.656   629.4 1576.68   664.4 1585.08   680.3 1591.18   711.9 1606.66
  771.291624.307   827.9 1641.61     844 1648.37   856.2 1656.77   873.2 1657.28
#Mann= 8 ,-1 , 0
       0      .1       0  213.08      .1       0   260.4     .05       0
  333.73      .1       0   420.6    .045       0   446.1      .1       0
  575.03      .1       0  771.29     .06       0
Bank Sta=420.6,446.1
XS Rating Curve= 0 ,0
Exp/Cntr=0.3,0.1

Type RM Length L Ch R = 1 ,2984    ,87.2,87.2,87.2
XS GIS Cut Line= 2
2446195.05512332699240.536388496 2445531.7739476698754.357175726
#Sta/Elev= 30
       0 1722.74    70.4 1717.04   124.5 1704.73     176 1679.62  280.711617.014
   341.1 1580.69   347.5 1572.54   372.3 1532.69   387.2 1515.46   396.3 1509.53
     412 1507.99   419.2 1509.22   426.9 1511.66   453.6 1512.16   466.6 1518.37
   476.5 1524.43   493.6 1543.98   516.2 1563.44     541 1581.22  563.851593.349
  567.421595.412   595.5 1611.52     651 1638.66     665 1642.25   685.4 1653.56
  705.191658.467   756.9 1677.73   780.9 1678.95   794.4 1689.18   822.4 1701.21
#Mann= 7 ,-1 , 0
       0      .1       0  280.71      .1       0   396.3    .045       0
   419.2      .1       0  563.85      .1       0  567.42      .1       0
  705.19     .06       0
Bank Sta=396.3,419.2
XS Rating Curve= 0 ,0
Exp/Cntr=0.3,0.1

Type RM Length L Ch R = 1 ,2897    ,201.3,201.3,201.3
XS GIS Cut Line= 2
2446221.07491463699205.2589492482445622.90512259698675.094539599
#Sta/Elev= 30
       0 1735.15    61.9 1726.21      88 1720.29   112.1 1710.85   211.6 1662.94
   329.2 1601.22   337.7  1592.4     349 1575.62  360.841562.306   383.5 1537.51
   401.6 1511.32     417 1502.52   419.9 1501.71   437.8 1503.19   443.8 1506.86
     468 1537.01   496.4 1564.72   505.5 1576.63   516.2 1583.46   528.2  1599.8
   546.3 1613.05  608.071650.542   633.8 1666.25   644.5 1669.36     679 1690.99
   691.1 1692.61   714.6 1691.66   734.71706.425   751.4 1712.14   799.3 1723.29
#Mann= 6 ,-1 , 0
       0      .1       0  360.84      .1       0     417    .045       0
   437.8      .1       0  608.07     .06       0   734.7      .1       0
Bank Sta=417,437.8
XS Rating Curve= 0 ,0
Exp/Cntr(USF)=0,0
Exp/Cntr=0.3,0.1

Type RM Length L Ch R = 1 ,2695    ,250.6,250.6,250.6
XS GIS Cut Line= 3
2446307.45819666699113.8688817952446043.43619666698784.934881795
2445780.31719666698474.054881795
#Sta/Elev= 30
       0 1718.41    73.8    1675    96.1 1660.09   164.8 1620.39     199 1597.34
  226.461574.803  262.681547.854   298.5 1522.51     3391496.584   358.3 1483.78
     401 1469.83   409.5 1468.22   422.9  1470.3   435.1  1476.6   449.3 1495.69
   461.1 1505.09     506  1519.8   546.7 1536.04   562.8 1544.67     590 1564.49
   608.6 1573.64   628.1 1577.88   676.7 1583.91     699 1590.57   717.9 1594.01
   733.1 1594.76   761.5 1600.71     782 1606.95   801.8 1608.15   829.1 1618.13
#Mann= 6 ,-1 , 0
       0      .1       0  226.46      .1       0  262.68      .1       0
     339      .1       0     401    .045       0   422.9      .1       0
Bank Sta=401,422.9
XS Rating Curve= 0 ,0
Exp/Cntr=0.3,0.1

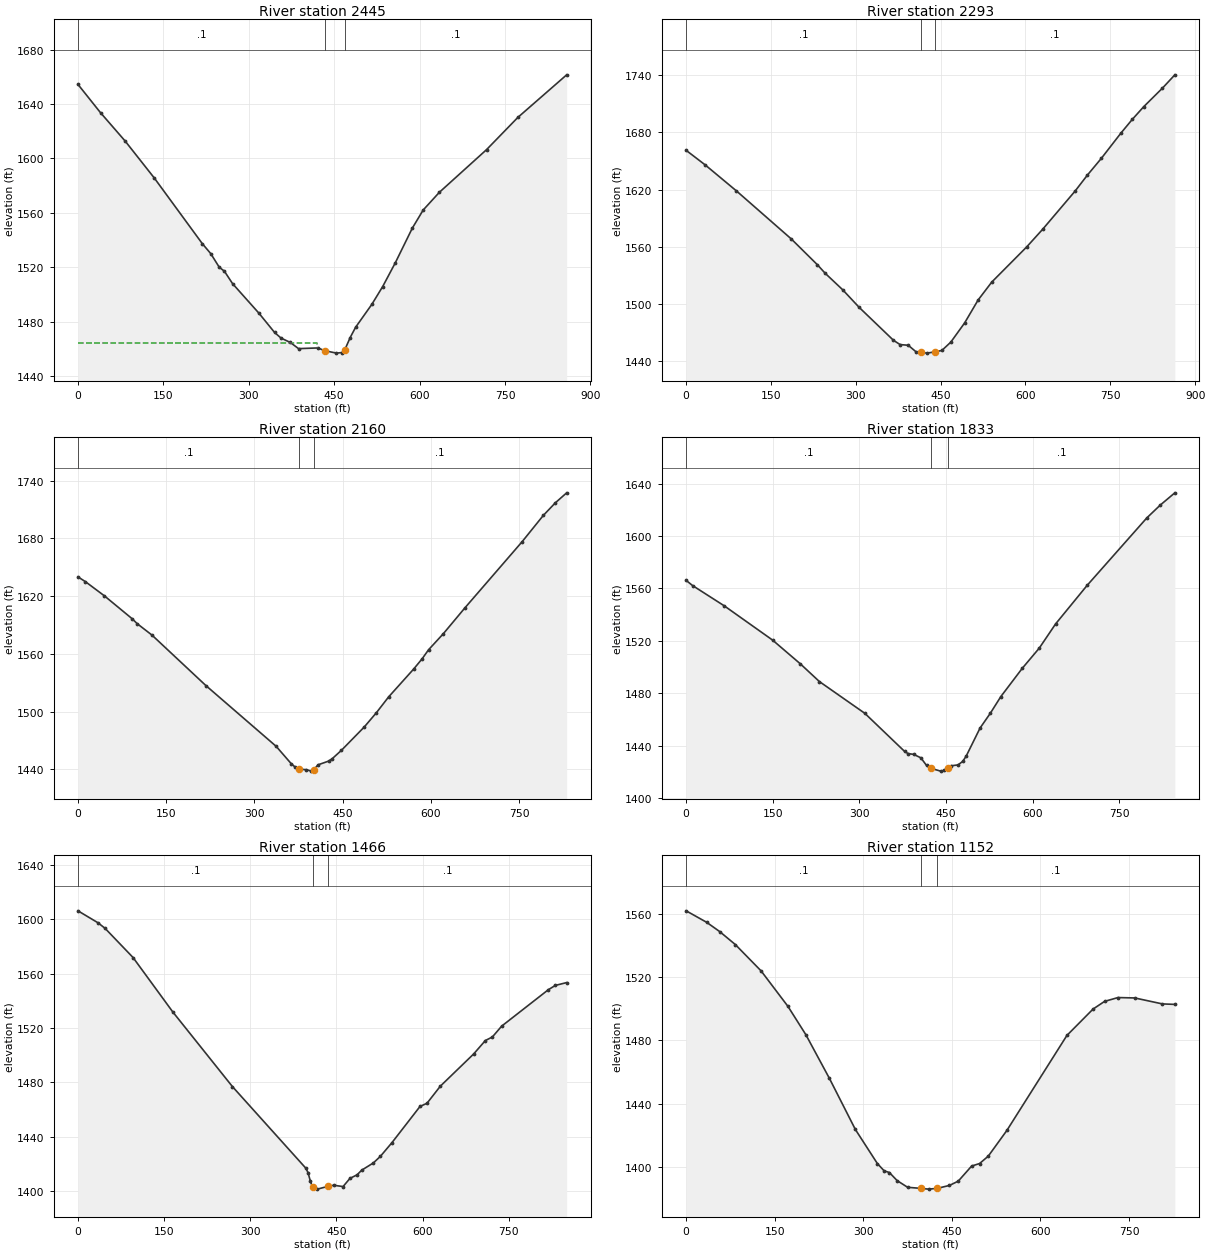
Type RM Length L Ch R = 1 ,2445    ,151.6,151.6,151.6
XS GIS Cut Line= 3
     2446513.796      698939.2082446355.34388496698722.279354616
     2445858.307      698405.044
#Sta/Elev= 30
       0  1654.5    39.6 1633.68    82.6 1612.95   134.1  1585.6   218.3 1537.37
   233.2 1529.99   248.1 1519.99   257.2 1517.04   271.5 1507.91   317.9 1486.12
   345.3 1471.99   356.7 1467.83   372.9 1464.64   387.4 1460.09   421.2  1460.6
   433.7 1458.56     454 1456.78   463.9 1457.23   468.2  1458.8   478.1 1468.27
   487.6 1475.81   516.1 1492.66   535.2 1505.78   557.5 1523.39   587.2 1548.75
   606.3 1562.08   634.7 1575.11   717.6 1606.51   772.6 1630.23   858.3 1661.55
#Mann= 3 ,-1 , 0
       0      .1       0   433.7    .045       0   468.2      .1       0
#XS Ineff= 2 , 0
           420.4 1464.58
Permanent Ineff=
       F       F
Bank Sta=433.7,468.2
XS Rating Curve= 0 ,0
Exp/Cntr=0.3,0.1

Type RM Length L Ch R = 1 ,2293    ,133.4,133.4,133.4
XS GIS Cut Line= 3
2446599.96204509698892.9893362352446411.21241233 698683.42172928
2446094.77920448698194.893268032
#Sta/Elev= 30
       0 1661.22    33.5    1646      89 1618.58   185.9 1568.19   231.8 1541.24
   245.9 1532.11   276.8 1514.81   305.9 1496.35   366.6 1461.75   378.2  1457.3
   392.7 1456.55   406.6 1449.63   416.1 1449.33   425.6 1448.31   439.9  1449.6
   452.1 1451.11   467.9 1459.83   492.4 1480.03   516.2 1504.08   540.4 1522.93
     602 1559.75   630.6 1578.51   687.8 1618.52   709.6 1635.34     734 1652.72
   768.8 1679.38   788.9 1693.77   809.2 1707.15   842.1  1726.5   864.1 1740.51
#Mann= 3 ,-1 , 0
       0      .1       0   416.1    .045       0   439.9      .1       0
Bank Sta=416.1,439.9
XS Rating Curve= 0 ,0
Exp/Cntr(USF)=0,0
Exp/Cntr=0.3,0.1

Type RM Length L Ch R = 1 ,2160    ,326.5,326.5,326.5
XS GIS Cut Line= 3
2446685.33270107698797.9179453732446430.86870107698480.424945373
2446161.54970107698153.118945373
#Sta/Elev= 30
       0 1640.02    12.5 1635.13    44.9 1620.32    92.2 1596.46   100.7 1591.37
   125.7 1579.56   217.4 1527.08   336.9 1463.89   362.5 1445.85   368.2 1442.81
   375.21440.218   388.3  1439.6   396.7 1438.12   400.7 1439.44   408.1 1444.67
     426 1448.53   432.3 1451.11   447.8 1459.74   486.6 1483.98   507.3 1498.87
     528 1515.23   570.8 1544.37     585 1554.89   595.9 1564.24   621.3 1581.14
   658.1 1608.09   754.8 1676.47   791.1 1703.99   811.6 1717.11   830.7  1727.4
#Mann= 3 ,-1 , 0
       0      .1       0   375.2    .045       0   400.7      .1       0
Bank Sta=375.2,400.7
XS Rating Curve= 0 ,0
Exp/Cntr=0.3,0.1

Type RM Length L Ch R = 1 ,1833    ,366.9,366.9,366.9
XS GIS Cut Line= 2
     2446896.444      698616.017     2446411.667      697922.401
#Sta/Elev= 30
       0 1566.12    11.1 1562.17    65.8 1546.74   149.6 1520.56   197.4 1502.53
   230.7 1488.89   309.4 1464.63   378.3 1435.53   384.1 1433.94     394 1433.28
   406.4 1430.67   416.2 1424.85   424.3 1422.58   440.6 1420.51   447.3 1421.08
     453    1423   458.8 1424.59   470.8 1425.25   478.9 1427.96   484.8 1431.91
   508.9  1453.4   526.7  1464.7   544.9 1477.43   582.1 1499.06   611.4  1514.4
   639.7 1532.89   694.2 1562.26   797.7 1613.84   821.2 1623.71   846.2 1632.96
#Mann= 3 ,-1 , 0
       0      .1       0   424.3    .045       0     453      .1       0
Bank Sta=424.3,453
XS Rating Curve= 0 ,0
Exp/Cntr=0.3,0.1

Type RM Length L Ch R = 1 ,1466    ,314.7,314.7,314.7
XS GIS Cut Line= 2
2447056.29616691 698589.290594842446907.02194537697751.497270107
#Sta/Elev= 30
       0 1606.31    34.9  1597.5    47.1 1593.45    95.9 1571.94     165 1531.94
   268.9 1476.95   396.6 1416.93   400.6 1413.61   404.7 1407.24   408.7 1402.81
   416.9 1401.44   436.1 1403.57   445.3 1404.29   461.6 1403.33   473.7 1409.39
   485.9 1411.94   494.1  1415.4   514.4 1420.73   526.6 1425.57   546.9 1435.73
   595.6  1462.3   607.8 1464.66     631 1477.23   689.1 1500.97   709.4 1510.83
   721.6 1513.44   737.8 1521.43   819.1 1548.25   831.3 1551.41     851 1553.49
#Mann= 3 ,-1 , 0
       0      .1       0   408.7    .045       0   436.1      .1       0
Bank Sta=408.7,436.1
XS Rating Curve= 0 ,0
Exp/Cntr=0.3,0.1

Type RM Length L Ch R = 1 ,1152    ,265.5,265.5,265.5
XS GIS Cut Line= 2
2447440.81054324698422.244971172 2447088.0346267697673.457672238
#Sta/Elev= 30
       0 1562.17    34.7  1554.9    56.8 1549.02    83.3 1540.79   126.9 1524.11
   172.4 1501.62   202.7 1483.69   242.5 1456.08   286.6  1423.6   323.9 1401.99
   335.3 1397.42   344.2 1396.33   357.4 1391.19   375.1 1386.97   397.8 1386.28
   410.5 1385.81   424.9 1386.27     446 1388.16   460.9 1390.89   483.5 1400.43
     497 1402.04   511.7 1406.72   543.2 1423.01   644.9 1483.22   689.1  1499.9
   708.7 1504.79   731.4 1507.21   759.8 1506.96   806.6 1503.18   827.7 1502.88
#Mann= 3 ,-1 , 0
       0      .1       0   397.8    .045       0   424.9      .1       0
Bank Sta=397.8,424.9
XS Rating Curve= 0 ,0
Exp/Cntr=0.3,0.1

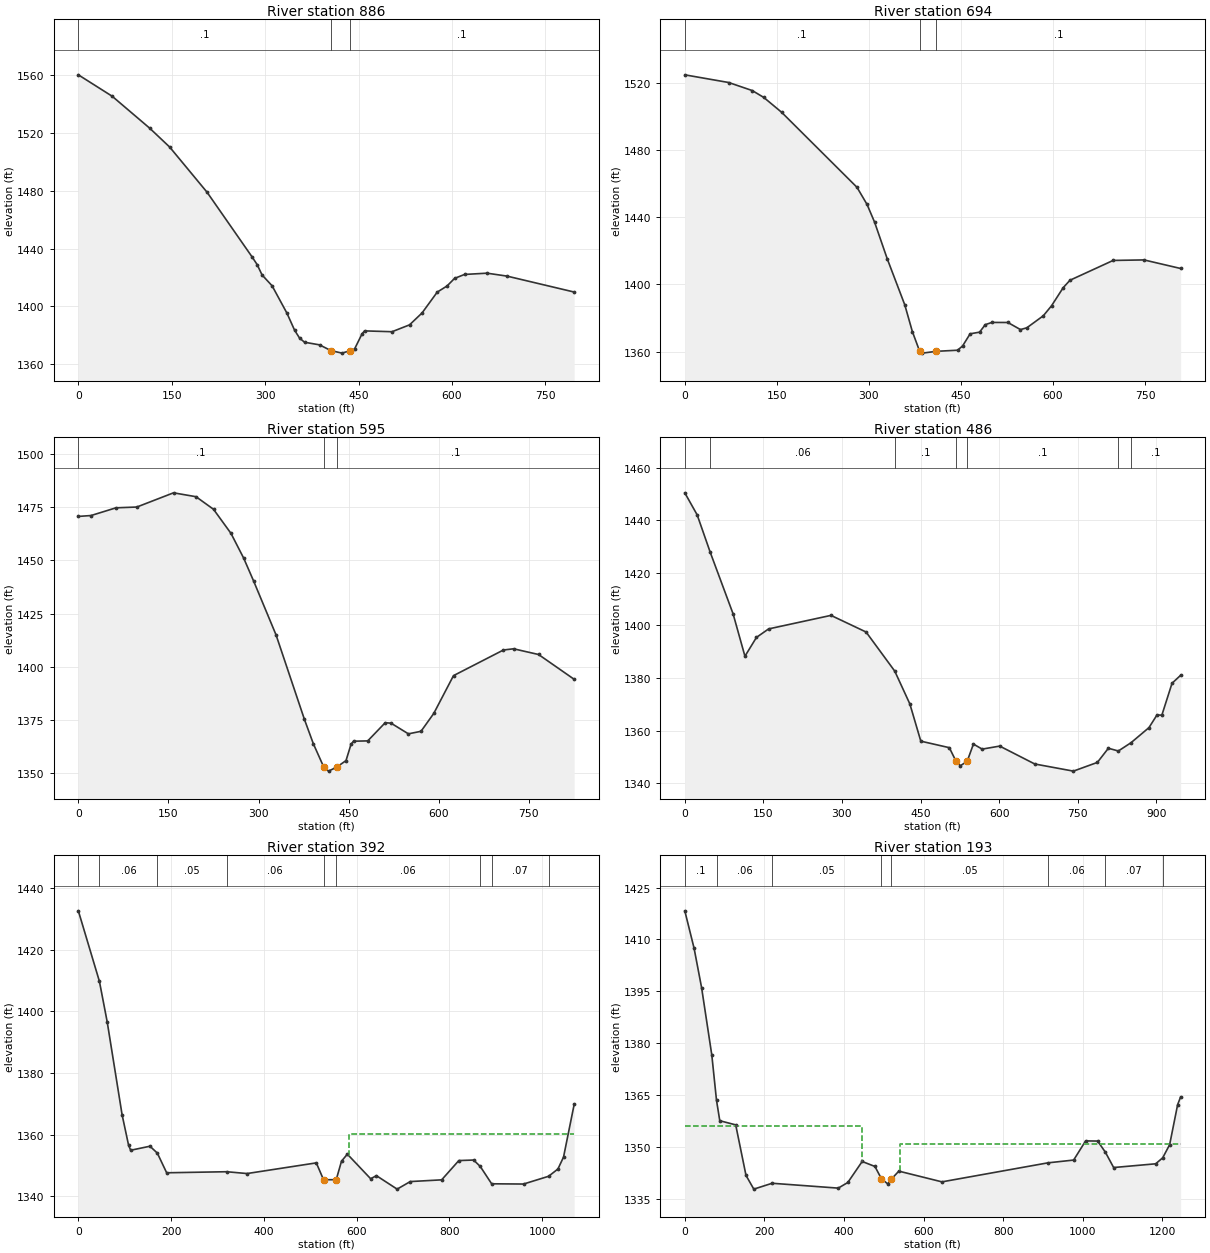
Type RM Length L Ch R = 1 ,886     ,192,192,192
XS GIS Cut Line= 2
     2447475.207      698424.9772447541.34356904697631.404083455
#Sta/Elev= 30
       0 1560.15    54.3 1545.36   114.5  1523.3   146.6 1510.25   206.8 1478.94
   279.1 1434.22   287.1    1429   295.1 1421.76   311.2 1414.28     335 1395.39
   347.3 1383.59   355.3 1378.14   363.3 1375.26   387.4 1373.45   405.6 1369.49
   423.5 1367.73   436.3 1369.42   443.6 1370.57   455.7  1381.1   459.7 1383.11
   503.8 1382.53   531.9 1387.27     552 1395.49   576.4 1409.92   592.1 1414.14
   604.2 1419.39   620.2 1422.13   656.4 1423.01   688.5 1420.98   796.3 1409.96
#Mann= 3 ,-1 , 0
       0      .1       0   405.6    .045       0   436.3      .1       0
Bank Sta=405.6,436.3
XS Rating Curve= 0 ,0
Exp/Cntr=0.3,0.1

Type RM Length L Ch R = 1 ,694     ,99.2,99.2,99.2
XS GIS Cut Line= 2
 2447778.7797575698428.6741349752447602.03437793 697640.22404327
#Sta/Elev= 30
       0 1524.74    71.5 1520.17   109.9 1515.38   128.8 1511.26   157.6 1502.51
   280.6  1457.8     297  1447.6   309.3 1437.03   329.8 1415.35   358.5 1387.84
   370.8 1371.99   382.7 1360.25   387.2 1359.12   410.1  1360.2   444.5 1360.85
   452.7  1363.4     465 1370.62   480.4  1371.6   489.6 1376.06   500.5 1377.39
   526.5 1377.35     547 1373.13   557.4  1374.2   584.2 1381.34   597.6 1387.28
   616.7  1398.1   627.7  1402.5     698 1414.28   748.3 1414.59     808 1409.49
#Mann= 3 ,-1 , 0
       0      .1       0   382.7    .045       0   410.1      .1       0
Bank Sta=382.7,410.1
XS Rating Curve= 0 ,0
Exp/Cntr(USF)=0,0
Exp/Cntr=0.3,0.1

Type RM Length L Ch R = 1 ,595     ,109.4,109.4,109.4
XS GIS Cut Line= 2
2447895.06421851698399.165890746     2447666.276      697605.918
#Sta/Elev= 30
       0 1470.69    21.1  1471.1    62.7 1474.73    97.4  1475.1   158.5 1481.78
   195.9 1479.96   225.1 1474.04   254.2  1462.7   275.4 1451.02   291.7 1440.42
   329.2 1414.99   376.4  1375.3   391.4 1363.74   408.3 1353.06   416.6 1350.92
   430.2  1352.8   445.7 1355.87   454.1 1363.56   458.2 1364.99   481.9 1365.14
     511 1373.69   520.7 1373.47   549.6 1368.45   570.6 1369.65   591.8 1378.03
   624.7 1395.82   707.8 1407.87   724.7 1408.44   766.3 1405.76   825.6  1394.1
#Mann= 3 ,-1 , 0
       0      .1       0   408.3    .045       0   430.2      .1       0
Bank Sta=408.3,430.2
XS Rating Curve= 0 ,0
Exp/Cntr=0.5,0.3

Type RM Length L Ch R = 1 ,486     ,93.8,93.8,93.8
XS GIS Cut Line= 4
2447954.80868998698470.6448526362448006.15969301698367.942846579
2447822.96152004697768.3851895942447696.66580989697607.392855774
#Sta/Elev= 30
       0 1450.38    23.6 1442.01    48.61427.762    92.2  1404.4   114.8 1388.31
   136.8 1395.47     160 1398.69     279 1403.83     346 1397.51  400.751382.658
   429.6 1370.18   450.5 1356.05   504.9 1353.58   517.5 1348.51   525.8 1346.72
   538.9 1348.35   550.9 1354.94   567.6 1353.03   601.1 1354.18     668 1347.38
   741.7 1344.67   787.5 1347.98   808.5 1353.36  827.511352.318  851.691355.458
     886  1361.2   901.2 1365.99   910.6 1365.94     930 1378.04   946.4 1381.07
#Mann= 7 ,-1 , 0
       0      .1       0    48.6     .06       0  400.75      .1       0
   517.5    .045       0   538.9      .1       0  827.51     .07       0
  851.69      .1       0
#XS Ineff= 2 , 0
             503  1352.3     555          1352.3
Permanent Ineff=
       F       F
Bank Sta=517.5,538.9
XS Rating Curve= 0 ,0
Exp/Cntr(USF)=0,0
Exp/Cntr=0.5,0.3

Type RM Length L Ch R = 1 ,392     ,199,199,199
XS GIS Cut Line= 5
2447986.72958376698492.8506917842448079.71653519698330.470493017
2447945.09363536697890.5173049062447927.05139105697758.670134967
2447700.82940473697579.635556839
#Sta/Elev= 30
       0  1432.6   45.431409.745    62.2 1396.63    94.4 1366.43   108.3 1356.63
   112.8 1354.98   154.4 1356.29  170.291354.058   190.4 1347.68  319.711348.021
   363.7 1347.43     513 1350.89   528.6 1345.42   555.9 1345.44   567.3 1351.44
   579.9 1353.72   630.1 1345.75   642.6 1346.74   687.2 1342.38   715.5 1344.83
   783.2 1345.39   820.2 1351.64   852.1 1351.81  866.441349.722  890.941344.109
   959.7 1344.03 1013.631346.542  1033.8  1348.9  1045.9 1352.77  1068.8 1369.83
#Mann= 9 ,-1 , 0
       0      .1       0   45.43     .06       0  170.29     .05       0
  319.71     .06       0   528.6    .045       0   555.9     .06       0
  866.44      .1       0  890.94     .07       0 1013.63      .1       0
#XS Ineff= 1 ,-1
  583.551068.781 1360.41
Permanent Ineff=
       F
Bank Sta=528.6,555.9
XS Rating Curve= 0 ,0
Exp/Cntr(USF)=0,0
Exp/Cntr=0.5,0.3

Type RM Length L Ch R = 1 ,193     ,,,
XS GIS Cut Line= 4
2448010.32328785698509.5050711452448174.09135157698291.610274509
2448147.72191758697880.8022502792447700.82940473697540.775338331
#Sta/Elev= 30
       0 1418.26    23.3 1407.46    42.2 1396.06    67.9 1376.55   79.65 1363.51
    87.9  1357.6   127.9  1356.4   153.8 1341.79   173.4 1337.83  219.451339.525
   385.5 1338.12   409.6 1339.75   445.7 1345.82   477.7 1344.38   493.8 1340.89
   509.8 1339.34  518.88 1340.71   537.8 1343.03   646.1 1339.93  912.341345.426
     977 1346.23  1007.1 1351.77  1037.3 1351.72 1056.561348.534  1077.5 1344.07
  1183.1 1345.15 1200.77 1346.88  1218.2 1350.67  1238.3 1362.25  1245.8 1364.47
#Mann= 8 ,-1 , 0
       0      .1       0   79.65     .06       0  219.45     .05       0
   493.8    .045       0  518.88     .05       0  912.34     .06       0
 1056.56     .07       0 1200.77      .1       0
#XS Ineff= 2 , 0
          444.06 1355.99  541.07         1350.96
Permanent Ineff=
       F       F
Bank Sta=493.8,518.88
XS Rating Curve= 0 ,0
Exp/Cntr(USF)=0,0
Exp/Cntr=0.3,0.1
LCMann Table=0

Chan Stop Cuts=-1
Use User Specified Reach Order=0
Composite Channel Slope=5